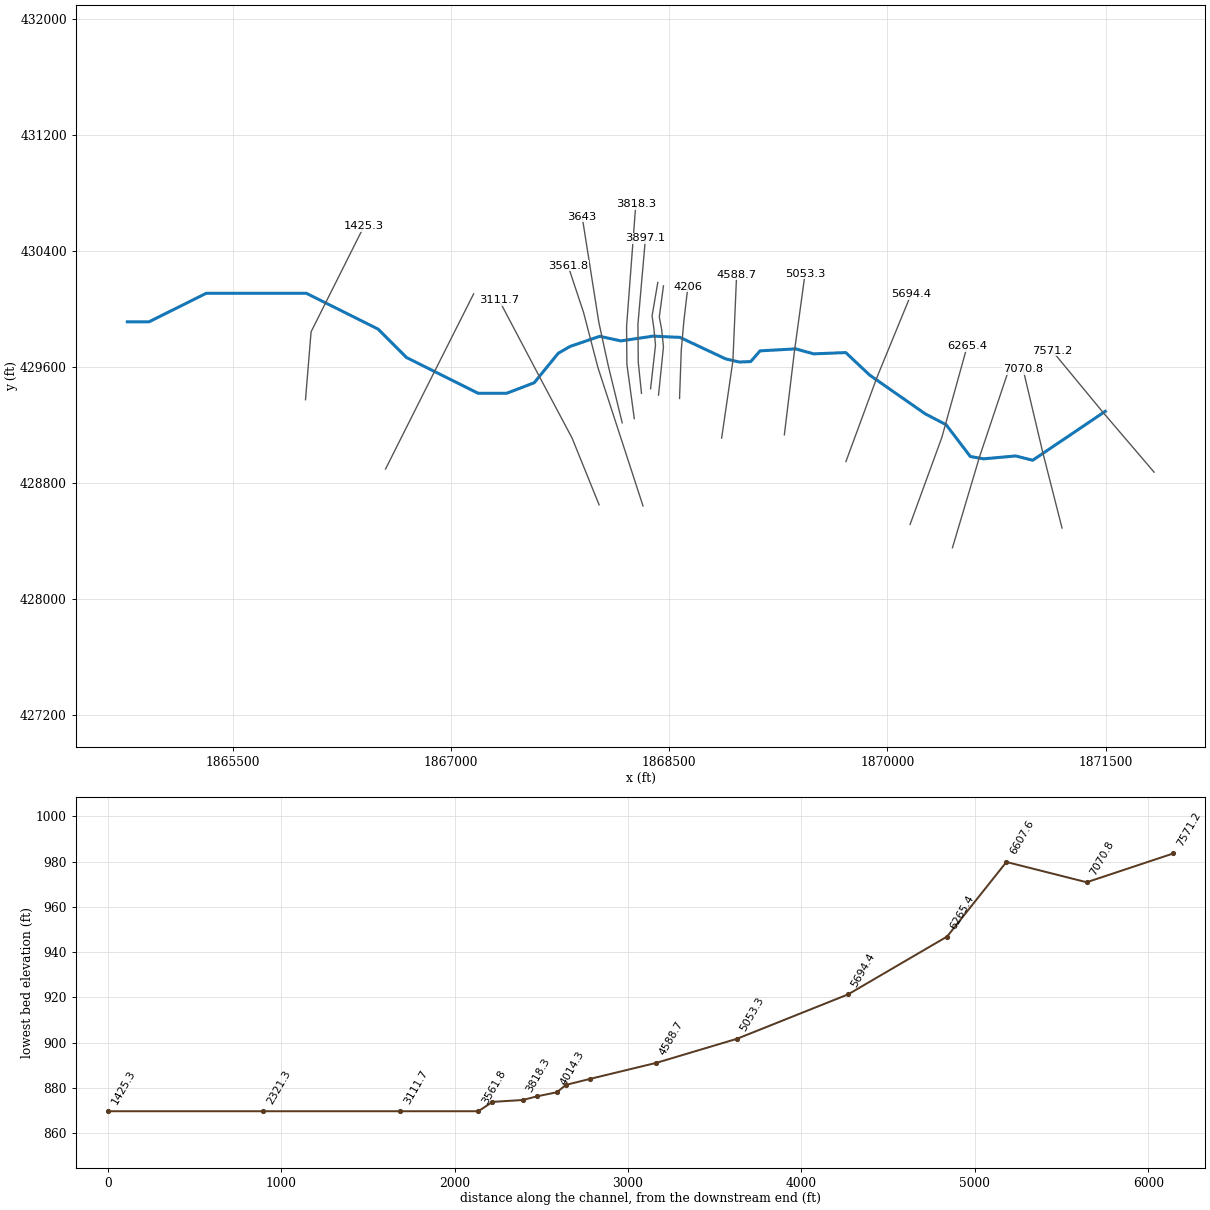
--- ColesRun.prj (project) ---

Proj Title=ColesRun
Current Plan=p01
Default Exp/Contr=0,0
English Units
Geom File=g01
Flow File=f01
Plan File=p01
BEGIN DESCRIPTION:
END DESCRIPTION:
DSS Export Rating Curves= 0
DSS Export Rating Curve Sorted= 0
DSS Export Volume Flow Curves= 0
DXF OffsetX= 0
DXF OffsetY= 0
DXF ScaleX= 0
DXF ScaleY= 0

--- ColesRun.p01 (plan) ---

Plan Title=Floodplain
Program Version=4.00
Geom File=g01
Flow File=f01
K Sum by GR=0
Std Step Tol=0.01
Critical Tol=0.01
Num of Std Step Trials=20
Max Error Tol=0.3
Flow Tol Ratio=0.001
Split Flow NTrial=30
Split Flow Tol=0.02
Split Flow Ratio=0.02
Log Output Level=0
Friction Slope Method=1
Unsteady Friction Slope Method=2
Unsteady Bridges Friction Slope Method=1
Global Log Level=0
CheckData=False
Run HTab=0
Run UNet=0
Run PostProcess=0
UNET Theta=0
UNET Theta Warmup=0
UNET ZTol=0
UNET ZSATol=0
UNET MxIter=0
UNET MaxInSteps=0
UNET DtIC=0
UNET DtMin=0
UNET MaxCRTS=0
UNET WFStab=0
UNET SFStab=0
UNET WFX=0
UNET SFX=0
UNET DSS MLevel=0
UNET DZMax Abort=0
UNET Convert EG Bridges=0
UNET Use Existing IB Tables=0
UNET Froude Limit=0
UNET Froude Power=0
Write IC File=0
Echo Input=False
Echo Output=False
Write Detailed=0

--- ColesRun.f01 (steady flow) ---

Flow Title=NFF Regression Equation
Program Version=4.10
Number of Profiles= 1
Profile Names=P100yr
River Rch & RM=ColesRun,Main            ,7571.2
     486
River Rch & RM=ColesRun,Main            ,7070.8
     539
River Rch & RM=ColesRun,Main            ,5053.3
     582
River Rch & RM=ColesRun,Main            ,3111.7
     724
River Rch & RM=ColesRun,Main            ,2321.3
     941
River Rch & RM=ColesRun,Main            ,1425.3
     969
Boundary for River Rch & Prof#=ColesRun,Main            , 1
Up Type= 0
Dn Type= 3
Dn Slope=0.01648
DSS Import GetInterval= 0
DSS Import GetPeak= 0
DSS Import FillOption= 0

--- ColesRun.g01 (geometry) ---

Geom Title=USGS 10m DEM
Program Version=4.10

River Reach=ColesRun        ,Main
Reach XY= 30
      1871497.95      429295.908     1870998.915      428958.687
     1870882.265      428988.344     1870660.827      428968.572
      1870569.88      428984.389     1870403.326      429203.771
     1870259.076      429278.981     1869877.724      429545.596
     1869713.469      429700.697     1869492.525       429692.08
     1869368.087       429726.35     1869123.601      429712.697
     1869059.582      429638.912     1868981.457      429635.657
     1868887.056      429657.358     1868572.718      429805.587
     1868387.878      429814.222     1868166.452      429781.259
     1868021.735      429812.957     1867817.568      429743.513
     1867735.548       429695.98     1867570.519      429493.051
     1867381.487      429420.526     1867184.639      429420.526
     1866692.519      429666.586     1866495.671      429863.434
     1866003.551      430109.494     1865314.583      430109.494
     1864920.887      429912.646     1864772.326      429912.954

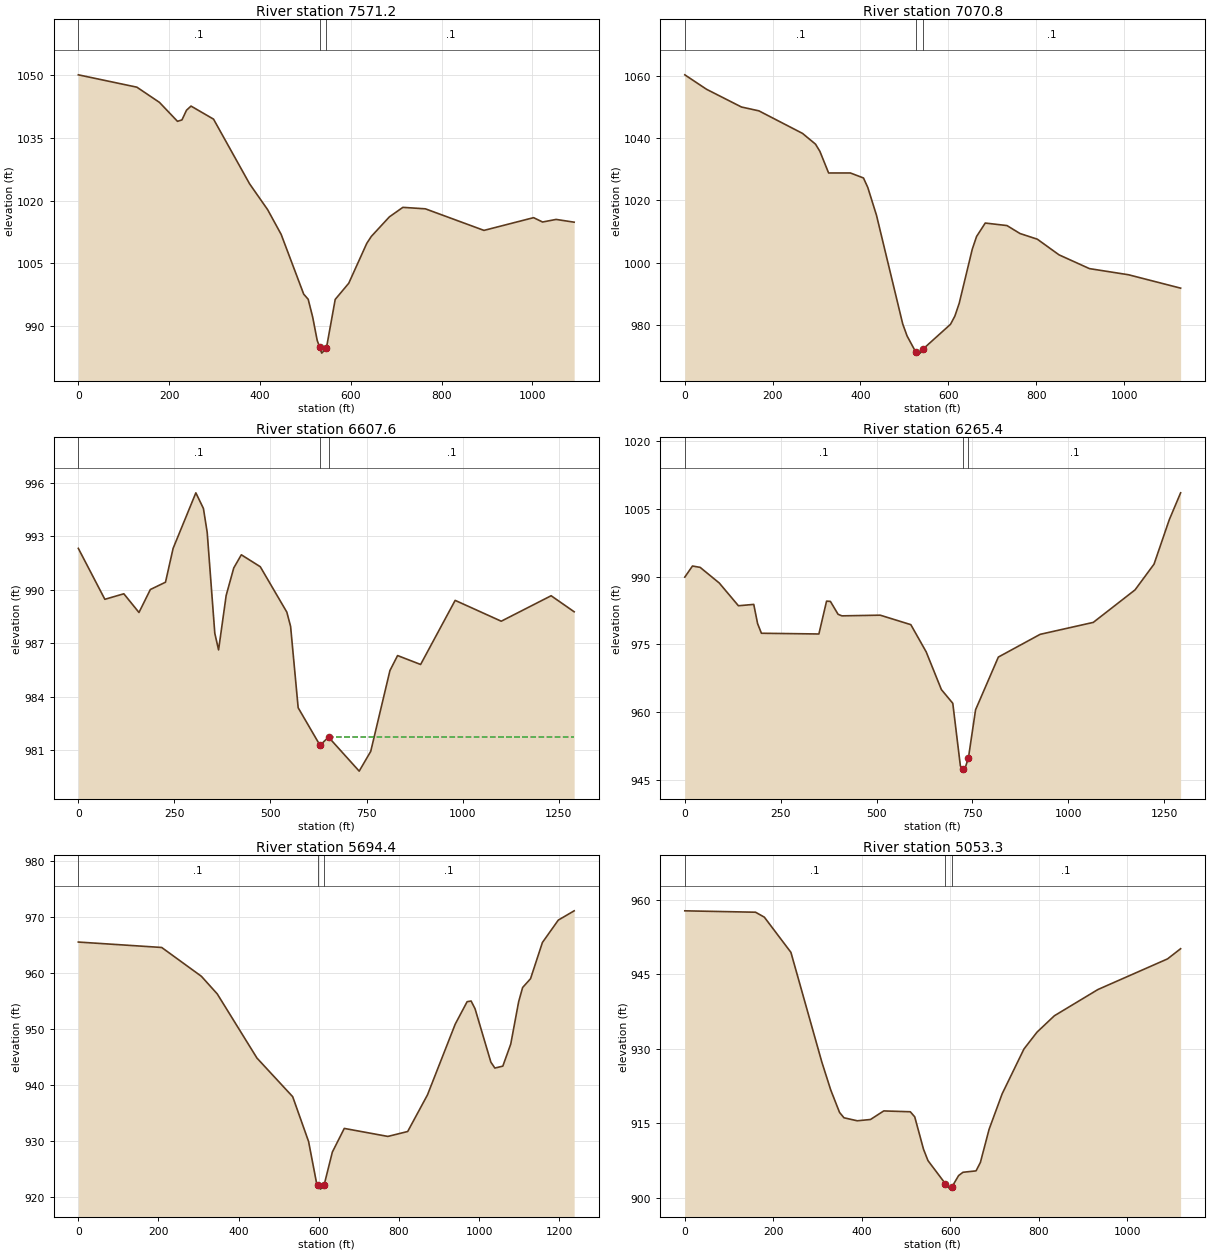
Type RM Length L Ch R = 1 ,7571.2  ,511.4,500.4,489.1
XS GIS Cut Line= 3
     1871833.705       428876.64     1871479.652      429292.267
     1871132.353      429713.688
#Sta/Elev= 30
       0 1050.04     129 1047.09   178.7 1043.46   218.4 1038.94   228.3 1039.28
   238.2 1041.58   248.2 1042.58   297.8 1039.46   377.2 1024.02   416.9 1017.86
   446.7 1011.96   496.4  997.68   506.3  996.45   516.2  992.19   526.1  986.66
   531.3  985.07   536.1   983.6   546.3  984.72   565.8  996.42   595.6 1000.28
   635.3  1009.8   645.3 1011.46     685 1016.12   714.8  1018.4   764.4 1018.05
   893.5  1012.9  1002.7 1015.94  1022.6  1014.9  1052.4 1015.52  1092.1 1014.86
#Mann= 3 , 0 , 0
       0      .1       0   531.3    .045       0   546.3      .1       0
Bank Sta=531.3,546.3
XS Rating Curve= 0 ,0
Exp/Cntr=0.3,0.1

Type RM Length L Ch R = 1 ,7070.8  ,474.7,463.1,451.4
XS GIS Cut Line= 3
     1871200.554      428491.574     1871068.595      429010.822
     1870932.258      429587.999
#Sta/Elev= 30
       0 1060.46    49.6  1055.8     129  1050.1   168.7 1048.86   267.9 1041.61
   297.6 1038.14   307.6 1035.81   327.4 1028.86     377 1028.86   406.8 1027.25
   416.7 1024.16   436.5  1015.2   496.1  980.28     506   976.4   525.8  971.21
   535.8  970.86   543.3  972.29   604.9  980.14   614.8  982.77   624.7  986.89
   654.4 1004.29   664.2  1008.4     684 1012.74   733.4 1011.93   763.1 1009.37
   802.6 1007.54     852  1002.5   921.2  998.07  1010.2  996.09  1128.8  991.78
#Mann= 3 , 0 , 0
       0      .1       0   525.8    .045       0   543.3      .1       0
Bank Sta=525.8,543.3
XS Rating Curve= 0 ,0
Exp/Cntr=0.3,0.1

Type RM Length L Ch R = 1 ,6607.6  ,340.9,342.2,342.8
XS GIS Cut Line= 3
     1870447.082      428356.157     1870632.559      428980.131
     1870835.309      429586.304
#Sta/Elev= 30
       0  992.32      69  989.46   118.4  989.77   157.8  988.72   187.4  990.01
   226.8  990.42   246.6  992.32   305.8  995.44   325.5  994.56   335.3  993.22
   355.1  987.55   364.9  986.62   384.7  989.68   404.4  991.22   424.1  991.96
   473.4  991.29   542.5  988.74   552.3  987.94     572  983.37  628.85  981.26
     651  981.72   730.8  979.81   760.8  980.92   810.8  985.46   830.7   986.3
   890.6   985.8   980.5   989.4  1100.4  988.23  1230.2  989.66  1290.1  988.76
#Mann= 3 , 0 , 0
       0      .1       0  628.85    .045       0     651      .1       0
#XS Ineff= 2 , 0
                          651.92          981.72
Permanent Ineff=
       F       F
Bank Sta=628.85,651
XS Rating Curve= 0 ,0
Exp/Cntr=0.3,0.1

Type RM Length L Ch R = 1 ,6265.4  ,574.2,571,568.6
XS GIS Cut Line= 3
     1870155.415      428515.879     1870374.165      429116.574
     1870548.615      429746.257
#Sta/Elev= 30
       0  989.88      20  992.34      40  992.04    89.9  988.57   139.8  983.53
   179.8  983.83   189.8  979.57   199.8  977.43   349.6  977.27   369.6  984.55
   379.6   984.5   399.6  981.64   409.5  981.29   509.4  981.44   589.3  979.34
   629.3  973.31     669  964.94   698.7   961.9   718.5  948.02   724.6  947.31
   728.4  946.86   739.6  949.87   758.1  960.46   817.5  972.15   926.4  977.19
    1065  979.84  1173.9  987.05  1223.4  992.76    1263 1002.58  1292.7 1008.57
#Mann= 3 , 0 , 0
       0      .1       0   724.6    .045       0   739.6      .1       0
Bank Sta=724.6,739.6
XS Rating Curve= 0 ,0
Exp/Cntr=0.3,0.1

Type RM Length L Ch R = 1 ,5694.4  ,635.6,641.1,646.4
XS GIS Cut Line= 3
     1869714.443      428949.907     1869926.249      429526.296
      1870162.36      430102.685
#Sta/Elev= 30
       0  965.48     208  964.51     307  959.36   346.6  956.21   445.7  944.74
   534.8  937.84   574.5  929.82   594.3  922.42     598  922.01   604.2  921.32
     613     922   633.8  927.95   663.5  932.17   772.3  930.74   821.7  931.62
   871.1  938.17   940.3  950.81     970  954.82   979.9  954.94   989.8  953.55
  1029.3     944  1039.2  942.96    1059   943.3  1078.8  947.24  1098.5   954.8
  1108.4  957.35  1128.2  958.93  1157.8   965.4  1197.4   969.4    1237  971.06
#Mann= 3 , 0 , 0
       0      .1       0     598    .045       0     613      .1       0
Bank Sta=598,613
XS Rating Curve= 0 ,0
Exp/Cntr=0.3,0.1

Type RM Length L Ch R = 1 ,5053.3  ,464.5,464.6,466.7
XS GIS Cut Line= 3
     1869290.832      429133.935     1869360.131      429709.276
      1869433.43      430245.267
#Sta/Elev= 30
       0  957.82   159.9  957.54   179.8  956.54   239.8  949.45   309.7  927.32
   329.7  921.72   349.7  917.17   359.7  916.09   389.7  915.48   419.6  915.74
   449.6  917.47   509.6   917.3   519.6  916.28   539.5  909.74   549.5  907.46
   588.5  902.83   599.2   901.7   603.5  902.11   618.8  904.44   628.7   905.1
   658.2  905.38     668  907.08   687.7  913.77   717.2  920.92   766.4  929.95
   795.9  933.35   835.2  936.66   933.6  941.95    1091  948.13  1120.5  950.18
#Mann= 3 , 0 , 0
       0      .1       0   588.5    .045       0   603.5      .1       0
Bank Sta=588.5,603.5
XS Rating Curve= 0 ,0
Exp/Cntr=0.3,0.1

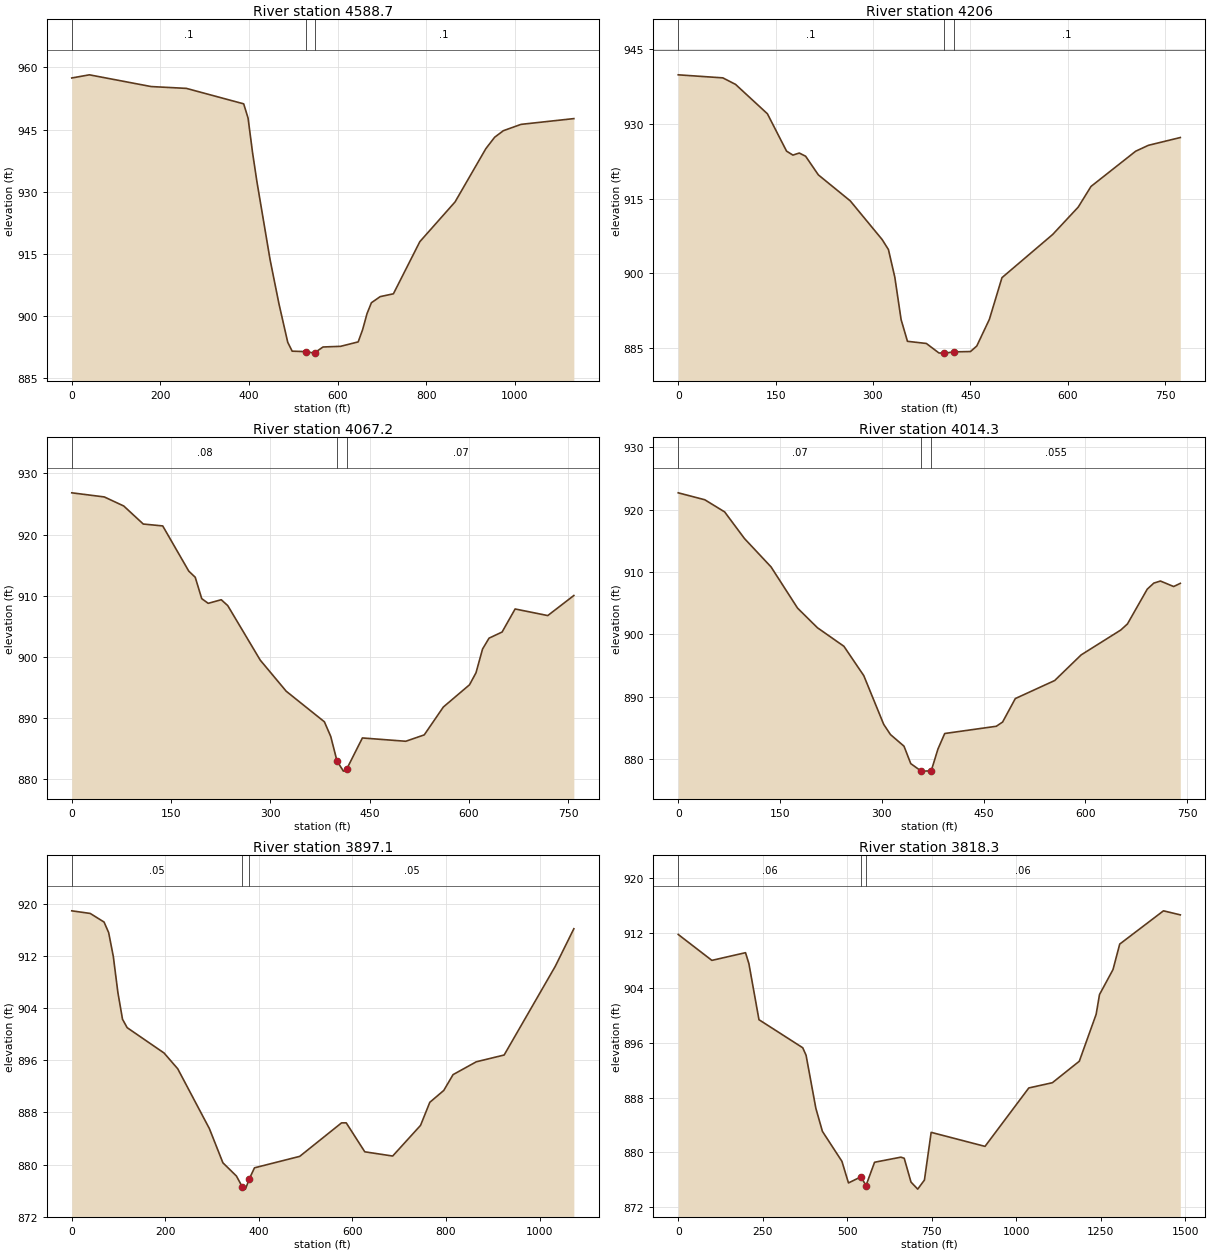
Type RM Length L Ch R = 1 ,4588.7  ,380.9,382.7,382
XS GIS Cut Line= 3
     1868859.525      429111.471     1868936.848      429643.062
     1868962.582      430238.454
#Sta/Elev= 30
       0  957.45    39.8  958.21   179.1  955.38   258.6  954.94     388  951.21
   397.9  947.77   407.9  939.52   417.8  932.48   447.6   913.6   467.6  902.97
   487.4  893.69   497.4  891.55   529.7  891.44   547.1  891.08  547.91  891.14
     567  892.56   606.7  892.72   646.4  893.79   656.4  896.74   666.3  900.59
   676.2  903.23   696.1  904.71   725.9  905.39   785.5  917.96     865  927.55
   934.5   940.4   954.4  943.16   974.2  944.74  1013.9  946.26  1133.1  947.65
#Mann= 3 , 0 , 0
       0      .1       0   529.7    .045       0  547.91      .1       0
Bank Sta=529.7,547.91
XS Rating Curve= 0 ,0
Exp/Cntr=0.3,0.1

Type RM Length L Ch R = 1 ,4206    ,134.7,138.8,142.8
XS GIS Cut Line= 4
     1868569.999      429384.702     1868581.848      429718.217
     1868600.077      429921.342      1868627.42      430155.717
#Sta/Elev= 30
       0  939.87    68.7  939.26    88.3  937.95   137.4  932.05   166.9  924.55
   176.7  923.75   186.5  924.17   196.3  923.52   215.9  919.78     265  914.57
   314.1  906.81   323.9  904.78   333.7  899.25   343.4  890.72   353.2  886.36
   382.3  885.93   401.7  884.02   409.2     884   411.4  883.99   424.2  884.24
   450.3  884.31     460  885.42   479.4  890.77   498.8  899.14     577  907.82
   616.3  913.31     636  917.46   704.8  924.53   724.5  925.72   773.6  927.28
#Mann= 3 , 0 , 0
       0      .1       0   409.2    .045       0   424.2      .1       0
Bank Sta=409.2,424.2
XS Rating Curve= 0 ,0
Exp/Cntr=0.3,0.1

Type RM Length L Ch R = 1 ,4067.2  ,53.1,52.8,52.6
XS GIS Cut Line= 5
     1868425.467      429408.139     1868459.321      429740.171
     1868446.301      429863.868     1868430.676        429945.9
     1868459.321      430160.743
#Sta/Elev= 30
       0  926.82    49.1  926.15    78.5  924.67     108  921.72   137.4  921.41
   176.7  914.03   186.5  913.02   196.3  909.53   206.1  908.76   225.8  909.35
   235.6  908.39   284.7  899.48   323.9   894.4   381.6   889.4   391.2     887
   400.7  882.98   410.3  881.34   415.7  881.76     439  886.76   504.5  886.22
   532.4  887.26   561.3  891.82   600.8  895.45   610.6  897.41   620.5  901.29
   630.3  903.07     650  904.07   669.7  907.84     719  906.76   758.4  910.04
#Mann= 3 , 0 , 0
       0     .08       0   400.7    .045       0   415.7     .07       0
Bank Sta=400.7,415.7
XS Rating Curve= 0 ,0
Exp/Cntr=0.3,0.1

Type RM Length L Ch R = 1 ,4014.3  ,119.2,117.2,115.3
XS GIS Cut Line= 5
      1868370.78      429451.108     1868404.634      429751.889
     1868394.217      429861.264     1868381.196      429953.712
     1868420.259      430184.181
#Sta/Elev= 30
       0  922.69    39.1  921.58    68.4  919.63    97.6  915.36   136.7  910.82
   175.8  904.21     205  901.07   244.1  898.09   273.4  893.38   302.7  885.58
   312.7  883.94   332.6  882.08   342.6  879.28   357.8   878.1   362.6  878.08
   372.8  878.15   382.6  881.61   392.6  884.11   468.6  885.27   477.9  885.95
   496.6  889.71   554.6   892.6   593.6  896.71     652   900.7   661.8  901.67
     691  907.25   700.7  908.22   710.4  908.55   729.9  907.67   739.7  908.18
#Mann= 3 , 0 , 0
       0     .07       0   357.8    .045       0   372.8    .055       0
Bank Sta=357.8,372.8
XS Rating Curve= 0 ,0
Exp/Cntr=0.3,0.1

Type RM Length L Ch R = 1 ,3897.1  ,78.7,78.8,78.7
XS GIS Cut Line= 4
      1868308.28      429419.954     1868285.927      429635.787
     1868283.757      429896.204     1868335.537      430489.838
#Sta/Elev= 30
       0  918.96    39.4  918.56      69  917.24    78.9  915.61    88.8  911.96
    98.6  906.41   108.5  902.31   118.4  901.02   197.3  897.13   226.6   894.7
   294.2  885.52   323.1  880.27     352  878.24   364.7  876.55   371.3  876.23
   379.7  877.84   390.6   879.5   487.3  881.26   576.7   886.4   586.7  886.41
   626.4  881.96     686  881.31   745.6  886.02   765.4  889.56   795.2  891.38
   815.1  893.81   864.7  895.78   924.3  896.82  1033.6  910.44  1073.3  916.21
#Mann= 3 , 0 , 0
       0     .05       0   364.7    .045       0   379.7     .05       0
Bank Sta=364.7,379.7
XS Rating Curve= 0 ,0
Exp/Cntr=0.3,0.1

Type RM Length L Ch R = 1 ,3818.3  ,170.2,175.3,180.1
XS GIS Cut Line= 4
     1868258.801      429245.474     1868207.802      429620.162
     1868205.632      429880.579     1868269.217      430724.641
#Sta/Elev= 30
       0  911.72    99.5  907.95     199  909.07     209  907.48   238.8  899.32
   368.2  895.24   378.1  894.15   407.1  886.42   426.4  883.08   484.2  878.71
   503.5  875.57   540.4  876.46   555.4  875.19   580.7  878.58   658.5  879.32
   668.4  879.16   688.4   875.7   708.3  874.67   728.2  875.99   748.1  882.93
   907.4  880.89  1036.9  889.39  1106.6  890.15  1186.3  893.28  1236.1  900.11
    1246  902.98  1285.9  906.61  1305.8  910.32  1435.2  915.16    1485  914.57
#Mann= 3 , 0 , 0
       0     .06       0   540.4    .045       0   555.4     .06       0
#XS Ineff= 2 , 0
                          658.82          879.26
Permanent Ineff=
       F       F
Bank Sta=540.4,555.4
XS Rating Curve= 0 ,0
Exp/Cntr=0.3,0.1

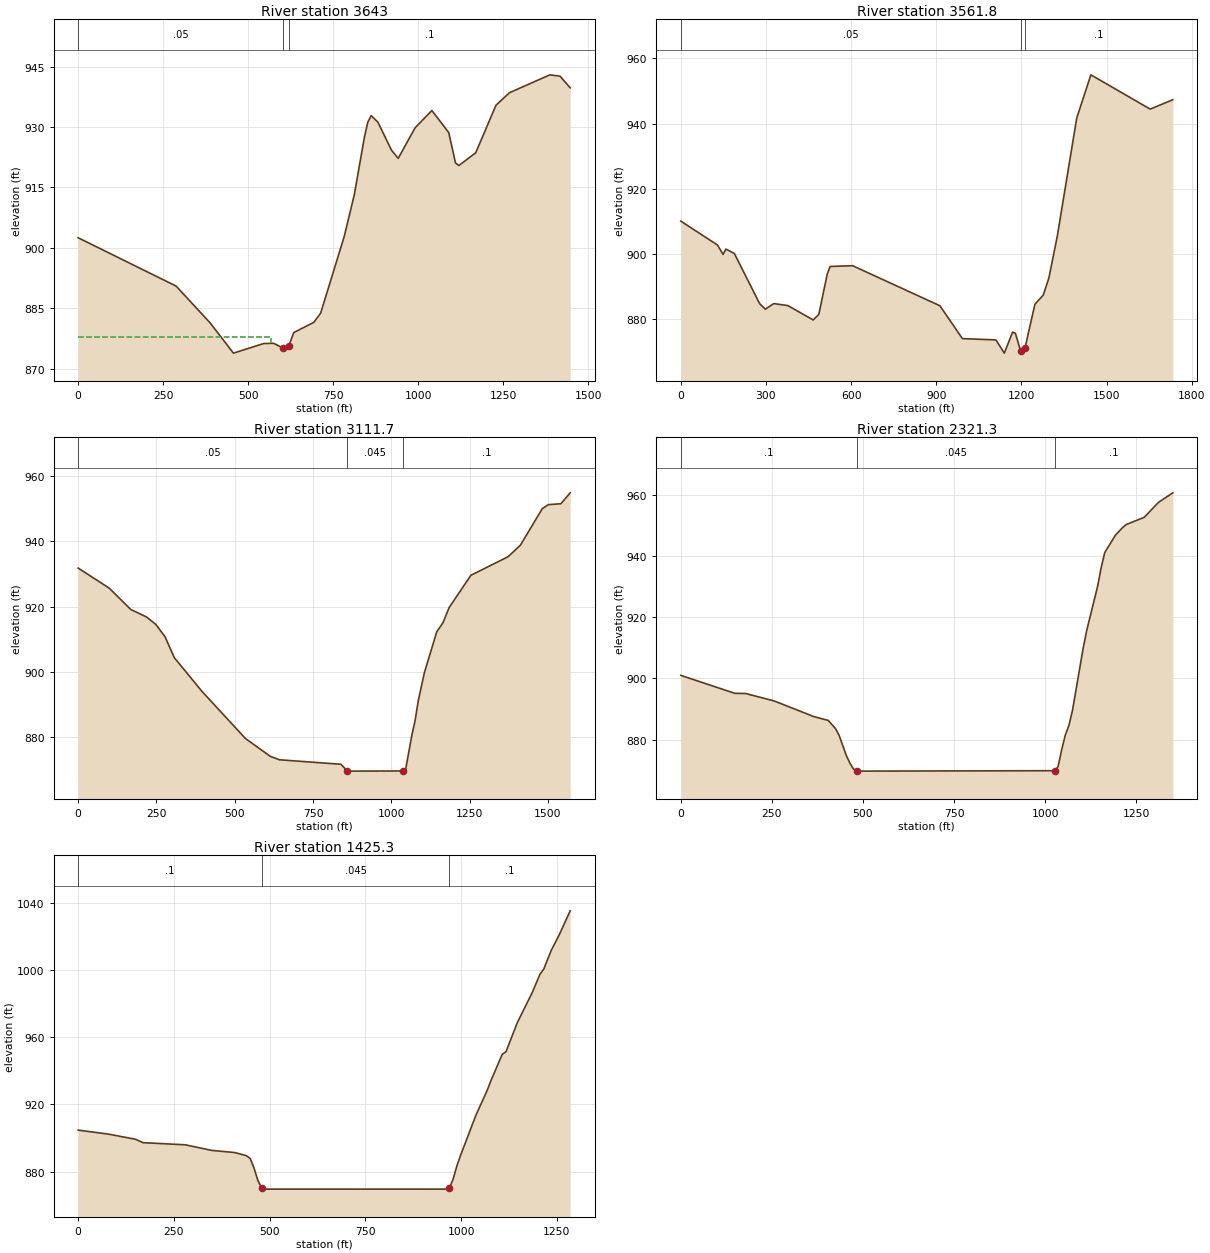
Type RM Length L Ch R = 1 ,3643    ,80.7,81.2,82.1
XS GIS Cut Line= 4
     1868175.467      429216.829     1868079.113      429612.662
     1868014.443       429911.36     1867900.294      430636.186
#Sta/Elev= 30
       0  902.49   288.2  890.48   387.5   881.4   456.7  873.83   545.4  876.21
     575  876.27   603.8  875.02   618.8  875.48   634.1  878.94   693.3   881.5
     713  883.75   782.4  902.79   812.2  913.25   841.9  927.53   851.8  931.22
   861.8  932.82   881.6  931.19   921.2  924.26   941.1  922.21   990.6  929.78
  1040.2   934.1  1089.8   928.6  1109.6  921.06  1119.6  920.44  1169.1   923.6
  1228.6   935.4  1268.3  938.52  1387.3  942.96    1417  942.62  1446.8  939.74
#Mann= 3 , 0 , 0
       0     .05       0   603.8    .045       0   618.8      .1       0
#XS Ineff= 2 , 0
          566.04  877.72
Permanent Ineff=
       F       F
Bank Sta=603.8,618.8
XS Rating Curve= 0 ,0
Exp/Cntr=0.3,0.1

Type RM Length L Ch R = 1 ,3561.8  ,445.2,450.1,454.9
XS GIS Cut Line= 4
     1868318.696      428643.912     1868008.801      429597.037
     1867909.842      429977.245     1867803.289       430298.72
#Sta/Elev= 30
       0  910.12     129  902.82   148.8  899.94   158.8  901.56   188.5  900.23
   277.8  884.84   297.7  883.16   327.5  884.87   377.1  884.26   466.4  879.86
   486.2  881.56     516  893.91   525.9  896.23   605.3  896.47   912.9  884.21
   992.3  874.14  1110.3  873.75  1139.8   869.7  1169.2  876.14    1179  875.78
  1197.7  870.27  1212.7  871.27  1247.8   884.7  1277.2  887.47  1296.9  892.69
  1326.4  905.41  1395.1  941.69  1444.9  954.92  1654.1  944.41  1733.8  947.31
#Mann= 3 , 0 , 0
       0     .05       0  1197.7    .045       0  1212.7      .1       0
#XS Ineff= 2 , 0
         1171.12  876.02
Permanent Ineff=
       F       F
Bank Sta=1197.7,1212.7
XS Rating Curve= 0 ,0
Exp/Cntr=0.3,0.1

Type RM Length L Ch R = 1 ,3111.7  ,811.9,790.3,768.8
XS GIS Cut Line= 4
     1868016.613      428651.724     1867831.198      429111.006
     1867605.669      429536.274     1867328.737      430062.029
#Sta/Elev= 30
       0  931.82    99.1  925.68   168.4  919.12   217.9  916.88   247.6  914.62
   277.4  910.81   307.1   904.4   396.2  894.01   534.6  879.64   613.2  874.25
   642.6  873.17   839.1   871.8   858.8  869.79   868.6   869.7 1037.35  869.75
    1046  870.46  1065.8  880.87  1075.7  885.09  1085.6  891.09  1105.4  899.82
    1145  912.34  1164.8  915.09  1184.6  919.76    1254  929.61  1372.8  935.29
  1412.4  938.86  1481.8  949.99  1501.6  951.22  1541.2  951.49  1570.9  954.83
#Mann= 3 , 0 , 0
       0     .05       0   858.8    .045       0 1037.35      .1       0
Bank Sta=858.8,1037.35
XS Rating Curve= 0 ,0
Exp/Cntr=0.3,0.1

Type RM Length L Ch R = 1 ,2321.3  ,896,896,896
XS GIS Cut Line= 3
     1866547.863      428898.252     1866879.609       429560.02
     1867153.679      430105.289
#Sta/Elev= 30
       0  900.99     148  895.13   177.7  895.07   256.6  892.62   365.2  887.52
   404.7  886.27   424.4  883.62   434.3  881.45     454  874.87   463.9  872.36
   473.8  870.42   483.6  869.76   493.5   869.7 1027.86  869.84  1035.6  871.27
  1045.4  876.72  1055.2  881.44  1065.1  884.57  1074.9   889.5  1104.5  909.99
  1114.3  915.78  1143.8  930.01  1153.7  936.16  1163.5  941.12    1193  946.83
  1212.7  949.32  1222.6  950.29  1271.8  952.64  1311.2  957.55  1350.5  960.65
#Mann= 3 , 0 , 0
       0      .1       0   483.6    .045       0 1027.86      .1       0
Bank Sta=483.6,1027.86
XS Rating Curve= 0 ,0
Exp/Cntr=0.3,0.1

Type RM Length L Ch R = 1 ,1425.3  ,1414.7,1425.3,1435.9
XS GIS Cut Line= 5
     1865997.429      429376.123     1866035.803      429843.915
     1866156.418      430085.144     1866263.928      430300.165
     1866400.596      430573.501
#Sta/Elev= 30
       0  904.77    79.9  902.36   149.8  899.34   169.8   897.3   279.6  896.04
   349.5   892.7   409.4  891.42   439.4  889.58   449.4  887.87   459.4  882.22
   469.4  874.91   479.4  870.37   489.3   869.7   960.2   869.7   969.8   870.3
   979.5   875.8   989.3  883.59   999.2  890.01  1038.6  913.44  1068.2   928.3
    1078  934.08  1107.6  949.77  1117.5  951.37    1147  968.61  1186.5  986.72
  1206.2  997.41  1216.1 1000.45  1235.8 1011.67  1255.5  1020.3  1285.1 1035.06
#Mann= 3 , 0 , 0
       0      .1       0   479.4    .045       0   969.8      .1       0
Bank Sta=479.4,969.8
XS Rating Curve= 0 ,0
Exp/Cntr=0.3,0.1

Chan Stop Cuts=-1
Use User Specified Reach Order=0
Composite Channel Slope=5